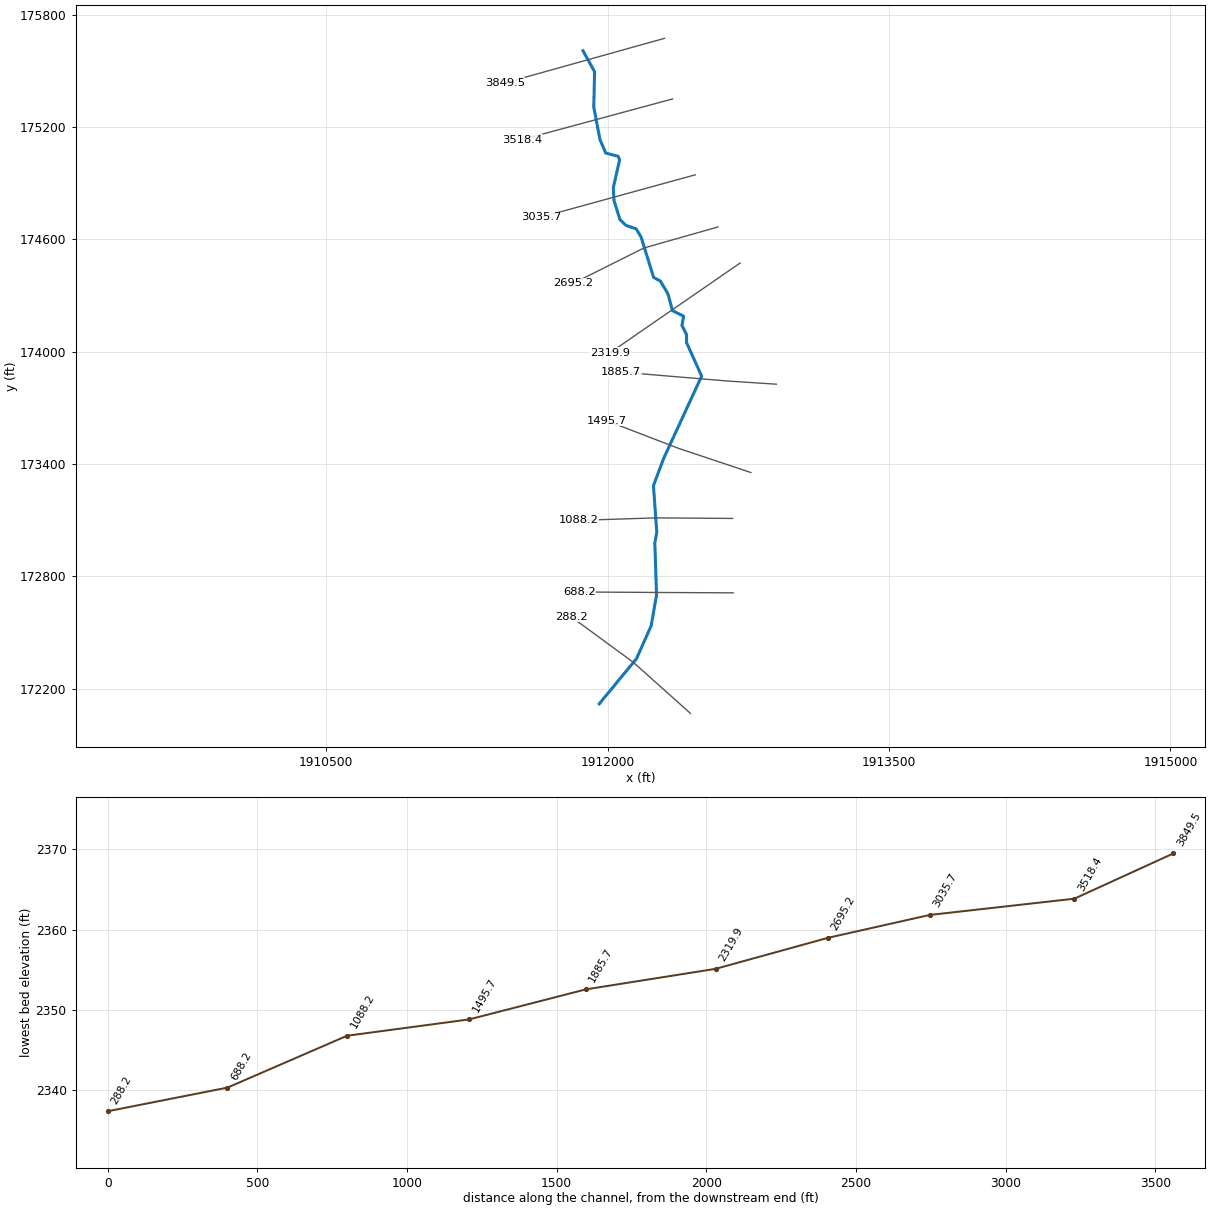
--- NP315.prj (project) ---

Proj Title=NP315
Current Plan=p01
Default Exp/Contr=0,0
English Units
Geom File=g01
Flow File=f01
Plan File=p01
BEGIN DESCRIPTION:
END DESCRIPTION:
DSS Export Rating Curves= 0
DSS Export Rating Curve Sorted= 0
DSS Export Volume Flow Curves= 0
DXF OffsetX= 0
DXF OffsetY= 0
DXF ScaleX= 0
DXF ScaleY= 0

--- NP315.p01 (plan) ---

Plan Title=Floodplain
Program Version=4.00
Geom File=g01
Flow File=f01
K Sum by GR=0
Std Step Tol=0.01
Critical Tol=0.01
Num of Std Step Trials=20
Max Error Tol=0.3
Flow Tol Ratio=0.001
Split Flow NTrial=30
Split Flow Tol=0.02
Split Flow Ratio=0.02
Log Output Level=0
Friction Slope Method=1
Unsteady Friction Slope Method=2
Unsteady Bridges Friction Slope Method=1
Global Log Level=0
CheckData=False
Run HTab=0
Run UNet=0
Run PostProcess=0
UNET Theta=0
UNET Theta Warmup=0
UNET ZTol=0
UNET ZSATol=0
UNET MxIter=0
UNET MaxInSteps=0
UNET DtIC=0
UNET DtMin=0
UNET MaxCRTS=0
UNET WFStab=0
UNET SFStab=0
UNET WFX=0
UNET SFX=0
UNET DSS MLevel=0
UNET DZMax Abort=0
UNET Convert EG Bridges=0
UNET Use Existing IB Tables=0
UNET Froude Limit=0
UNET Froude Power=0
Write IC File=0
Echo Input=False
Echo Output=False
Write Detailed=0

--- NP315.f01 (steady flow) ---

Flow Title=NFF Regression Equation
Program Version=4.00
Number of Profiles=1
Profile Names=P100yr
River Rch & RM=NP315,Main      ,3849.5
651.5766
River Rch & RM=NP315,Main      ,3518.4
674.9006
River Rch & RM=NP315,Main      ,1495.7
743.7122
River Rch & RM=NP315,Main      ,288.2
764.4173
Boundary for River Rch & Prof#=NP315,Main      ,1
Up Type=0
Dn Type=3
Dn Slope=0.009496

--- NP315.g01 (geometry) ---

Geom Title=USGS 3m DEM
Program Version=4.10

River Reach=NP315           ,Main
Reach XY= 30
     1911868.986      175607.226     1911930.791      175495.016
      1911926.41      175306.965      1911958.87      175134.592
      1911990.12      175060.373     1912056.526      175043.446
     1912064.339      175025.217     1912030.485      174875.478
     1912034.391      174806.467     1912065.641      174706.207
     1912096.891      174674.957     1912152.881      174655.426
     1912178.922      174611.155     1912245.329      174396.311
     1912281.787      174376.779     1912322.152      174307.769
       1912345.9      174218.524     1912405.485       174189.28
      1912396.37      174139.801     1912421.096      174090.478
     1912421.096      174047.929      1912501.42      173869.112
     1912299.342      173430.376     1912244.507      173284.149
     1912262.256      173035.634     1912251.839      172978.342
     1912260.954      172699.696     1912232.308      172535.634
     1912154.183      172359.852     1911955.351      172118.425

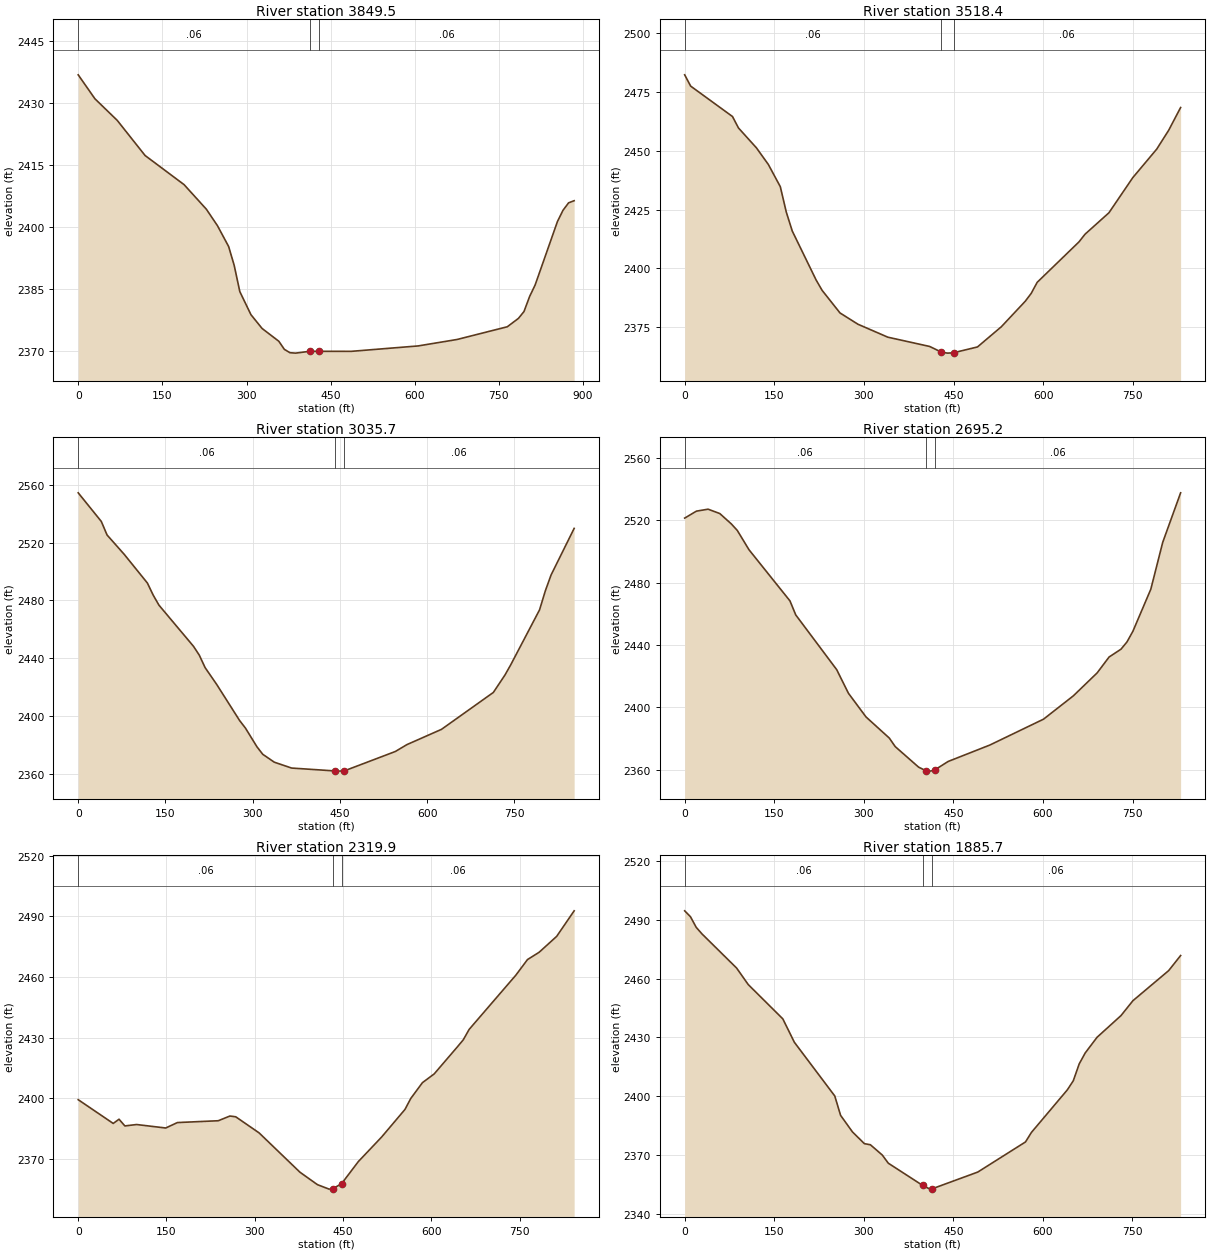
Type RM Length L Ch R = 1 ,3849.5  ,331.5,331.4,331.4
XS GIS Cut Line= 2
     1912303.573      175673.482     1911452.209      175435.186
#Sta/Elev= 30
       0 2436.75    29.8 2430.96    69.5 2425.75   119.2 2417.25   188.7 2410.21
   228.5 2404.26   248.3 2400.27   268.2 2395.24   278.1 2390.67   288.1 2384.35
   307.9 2378.78   327.8 2375.44   357.6 2372.35   367.5 2370.39   377.5 2369.58
   387.4 2369.48   413.6 2369.93   428.6 2369.92   486.7 2369.91     606 2371.22
   675.5 2372.78   764.9 2375.85   784.8 2377.88   794.7 2379.54   804.6 2383.14
   814.6 2385.97   854.3 2401.28   864.2    2404   874.2 2405.81   884.1 2406.32
#Mann= 3 , 0 , 0
       0     .06       0   413.6    .045       0   428.6     .06       0
Bank Sta=413.6,428.6
XS Rating Curve= 0 ,0
Exp/Cntr=0.3,0.1

Type RM Length L Ch R = 1 ,3518.4  ,482.4,482.6,482.3
XS GIS Cut Line= 2
     1912346.783      175349.833     1911545.876      175132.884
#Sta/Elev= 30
       0 2482.37      10 2477.57      80 2464.61      90 2459.74     120 2451.29
     140 2444.19     160 2434.74     170 2423.92     180 2415.85   219.9    2395
   229.9  2390.6   259.9 2380.95   289.9 2376.15   339.9 2370.63   409.9 2366.68
   429.7 2364.25   439.9 2363.84   449.9    2364   489.9 2366.47   529.8 2375.07
   569.8 2385.92   579.8 2389.28   589.8 2393.99   659.8 2411.23   669.8 2414.47
   709.8  2423.6   749.8 2438.59   789.8 2450.72   809.8 2458.74   829.8 2468.45
#Mann= 3 , 0 , 0
       0     .06       0   429.7    .045       0   449.9     .06       0
Bank Sta=429.7,449.9
XS Rating Curve= 0 ,0
Exp/Cntr=0.3,0.1

Type RM Length L Ch R = 1 ,3035.7  ,339.7,340.4,345.6
XS GIS Cut Line= 2
     1912467.222      174944.363     1911645.012      174718.135
#Sta/Elev= 30
       0 2554.39    39.7 2534.59    49.6 2525.23    79.3 2511.73     119 2491.95
   128.9 2483.64   138.8 2476.68   198.3 2448.16   208.2 2442.08   218.2 2433.44
     238 2421.89   277.6  2396.8   287.6 2391.58   307.4 2378.64   317.3 2373.49
   337.1 2368.02   366.9 2363.95   442.1 2361.93   446.2 2361.82   457.1 2361.92
   545.4 2375.42   565.2 2380.16   624.7 2390.73   713.9 2416.28   733.8 2428.31
   743.7 2435.35   793.3 2473.41   803.2  2486.5   813.1 2497.53   852.8 2529.78
#Mann= 3 , 0 , 0
       0     .06       0   442.1    .045       0   457.1     .06       0
Bank Sta=442.1,457.1
XS Rating Curve= 0 ,0
Exp/Cntr=0.3,0.1

Type RM Length L Ch R = 1 ,2695.2  ,367,375.3,379
XS GIS Cut Line= 3
     1912588.145       174665.98     1912192.652      174553.171
     1911818.006      174365.338
#Sta/Elev= 30
       0 2521.39    19.6 2525.85    39.2 2527.12    58.8 2524.32    78.3 2517.59
    88.1 2513.48   107.7 2501.08   176.3 2468.25     186 2459.24   254.6 2424.08
   274.2 2408.95   303.6 2393.77   342.7 2380.16   352.5 2374.73   391.7 2361.52
   403.8 2359.25   411.3 2358.97   418.8 2359.76   441.2 2365.18     511 2375.72
   600.9 2392.33   650.8  2407.3   690.7 2422.05   710.6 2432.21   730.6 2437.26
   740.6 2441.91   750.5 2448.75   780.5 2475.74   800.4  2505.8   830.4 2537.62
#Mann= 3 , 0 , 0
       0     .06       0   403.8    .045       0   418.8     .06       0
Bank Sta=403.8,418.8
XS Rating Curve= 0 ,0
Exp/Cntr=0.3,0.1

Type RM Length L Ch R = 1 ,2319.9  ,448.8,434.1,419.1
XS GIS Cut Line= 2
     1912706.508       174473.34     1912013.134       173994.17
#Sta/Elev= 30
       0 2399.31    59.5 2387.58    69.4 2389.66    79.3 2386.34    99.2 2387.04
   148.7 2385.32   168.6 2388.01     238 2388.91   257.8 2391.24   267.7 2390.86
   307.4 2382.91   376.8 2363.48   406.5 2357.33   426.4 2355.11   432.7 2355.29
   447.7 2357.84     476 2368.71   515.6 2380.85   555.3  2394.5   565.2 2399.94
     585 2407.74   604.9 2412.04   644.5 2425.47   654.4 2428.92   664.4 2434.07
   743.7 2460.85   763.5 2468.57   783.3 2472.18   813.1 2480.04   842.8 2492.66
#Mann= 3 , 0 , 0
       0     .06       0   432.7    .045       0   447.7     .06       0
Bank Sta=432.7,447.7
XS Rating Curve= 0 ,0
Exp/Cntr=0.3,0.1

Type RM Length L Ch R = 1 ,1885.7  ,396.7,389.9,383.2
XS GIS Cut Line= 3
     1912899.871      173826.034     1912639.353      173842.941
     1912071.777        173890.6
#Sta/Elev= 30
       0 2494.58     9.7 2491.58    19.3 2486.16      29  2482.8      87 2465.37
   106.4 2456.97   164.4 2439.43   183.7  2427.5   251.4 2400.08   261.1 2390.22
     281 2381.75     301 2375.75     311 2375.21     331 2369.93     341 2365.79
   398.7 2354.41     411 2352.55   413.7 2352.63   490.9 2361.26   570.8 2376.63
   580.8 2381.51   640.8 2403.18   650.8 2407.82   660.8 2416.48   670.8 2422.04
   690.7 2430.06   730.7  2441.1   750.7 2448.71   810.6 2464.07   830.6 2471.76
#Mann= 3 , 0 , 0
       0     .06       0   398.7    .045       0   413.7     .06       0
Bank Sta=398.7,413.7
XS Rating Curve= 0 ,0
Exp/Cntr=0.3,0.1

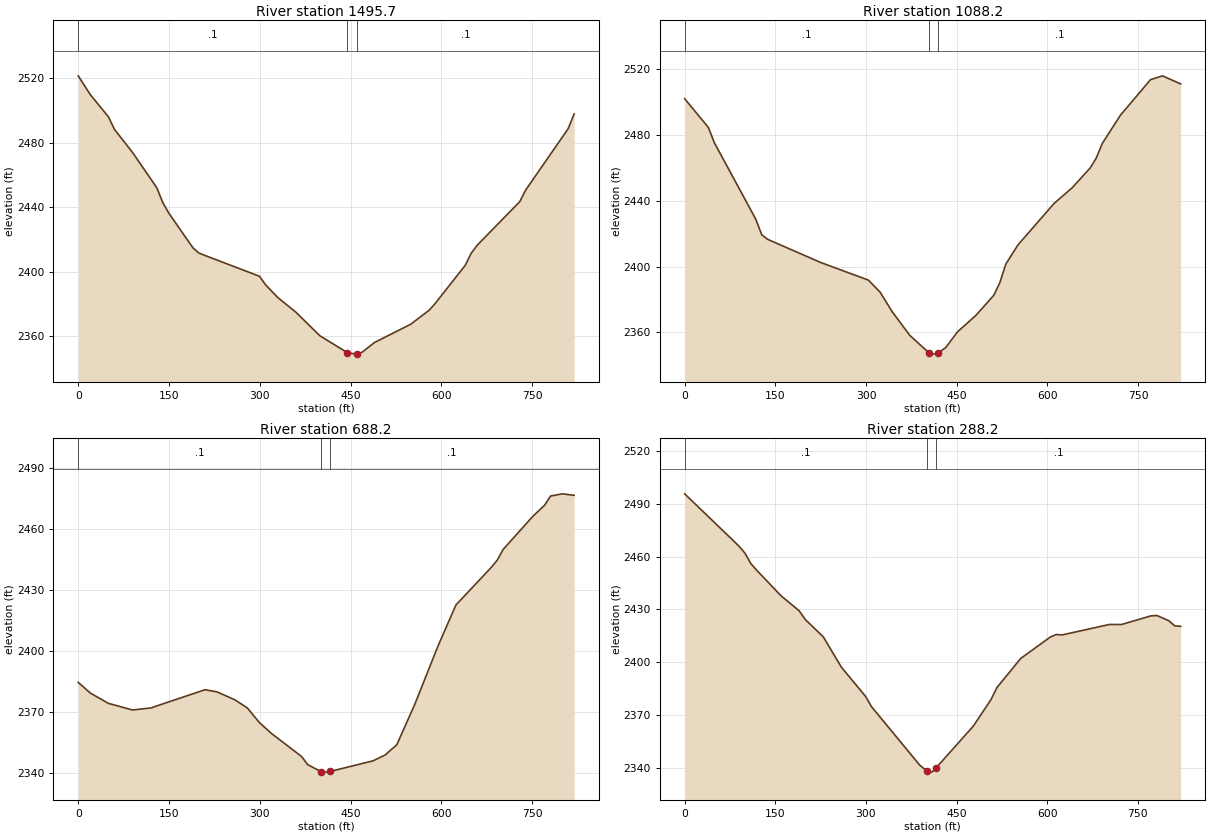
Type RM Length L Ch R = 1 ,1495.7  ,399.4,407.6,416.6
XS GIS Cut Line= 3
     1912764.112        173354.1     1912375.919      173484.197
     1911993.367      173631.673
#Sta/Elev= 30
       0 2521.62      20 2509.94    49.9 2496.18    59.9 2488.39    89.9 2473.98
   129.8 2452.15   139.8 2442.89   149.8  2436.3   189.7 2414.76   199.7 2411.49
   299.6 2397.13   309.6 2391.83   329.5 2384.02   359.5 2374.91   399.4 2360.18
   444.8 2349.72   459.4 2348.81   459.8 2348.86   469.4 2350.07   489.4    2356
   549.4 2367.38   579.4 2375.93   589.4 2380.06   639.4 2403.94   649.4 2411.49
   659.4 2416.51   729.4 2443.44   739.4 2450.75   809.4 2488.72   819.4 2497.97
#Mann= 3 , 0 , 0
       0      .1       0   444.8    .045       0   459.8      .1       0
Bank Sta=444.8,459.8
XS Rating Curve= 0 ,0
Exp/Cntr=0.3,0.1

Type RM Length L Ch R = 1 ,1088.2  ,399.8,399.8,399
XS GIS Cut Line= 3
     1912667.423      173108.964     1912255.787      173111.963
     1911847.122      173098.585
#Sta/Elev= 30
       0 2502.02    39.2 2484.59      49 2475.36   117.6 2428.84   127.4 2419.39
   137.2 2416.56   225.4 2402.43   303.8  2391.8   323.4 2384.43     343 2372.75
   372.4  2358.2   404.1 2347.59   411.6 2346.78   419.1 2347.55   431.6 2350.62
   451.5 2360.37   481.5 2370.22   511.4 2382.54   521.4 2390.21   531.3 2401.48
   551.3 2413.12   611.1 2438.37     641 2447.87   670.9 2459.95   680.9 2465.93
   690.9 2474.83   720.8 2491.95   770.7 2513.62   790.6 2515.95   820.5 2511.02
#Mann= 3 , 0 , 0
       0      .1       0   404.1    .045       0   419.1      .1       0
Bank Sta=404.1,419.1
XS Rating Curve= 0 ,0
Exp/Cntr=0.3,0.1

Type RM Length L Ch R = 1 ,688.2   ,416.4,399.9,385.7
XS GIS Cut Line= 3
     1912669.316      172711.549     1912260.182      172713.585
     1911849.712      172716.067
#Sta/Elev= 30
       0 2384.51      20 2379.24    49.9 2374.16    89.8 2370.91   119.8 2371.89
   209.6 2380.88   229.5 2379.81   259.4 2375.84   279.4 2371.93   299.4 2364.73
   319.3 2359.37   369.2 2347.99   379.2 2344.01   401.6 2340.52   409.1 2340.32
   416.6 2340.67   487.3 2345.88   506.9  2348.7   526.4 2353.75   555.7  2373.3
   594.8 2402.53   624.2 2422.58   682.8 2441.13   692.6 2444.68   702.3 2449.94
   751.2 2466.17   770.8 2471.69   780.5 2476.19   800.1 2477.29   819.6 2476.56
#Mann= 3 , 0 , 0
       0      .1       0   401.6    .045       0   416.6      .1       0
Bank Sta=401.6,416.6
XS Rating Curve= 0 ,0
Exp/Cntr=0.3,0.1

Type RM Length L Ch R = 1 ,288.2   ,288.9,288.2,285.3
XS GIS Cut Line= 3
     1912441.683      172067.689     1912136.975      172340.643
     1911805.014      172584.414
#Sta/Elev= 30
       0 2495.75    89.8 2466.02    99.8 2461.95   109.8 2455.94   119.7 2452.09
   159.6 2437.72   189.6 2429.16   199.6 2424.24   229.5 2414.35   259.4 2397.09
   299.3 2380.54   309.3 2374.61   389.1 2341.34   401.6 2337.88   409.1 2337.38
   416.6 2339.98   477.7 2363.55   507.1 2378.71     517 2385.58   556.2 2402.06
   605.2 2414.26     615 2415.69   624.8 2415.46   703.3 2421.42   722.9 2421.37
   771.9  2426.3   781.7 2426.51   801.3 2423.55   811.1 2420.64   820.9 2420.35
#Mann= 3 , 0 , 0
       0      .1       0   401.6    .045       0   416.6      .1       0
Bank Sta=401.6,416.6
XS Rating Curve= 0 ,0
Exp/Cntr=0.3,0.1

Chan Stop Cuts=-1
Use User Specified Reach Order=0
Composite Channel Slope=5